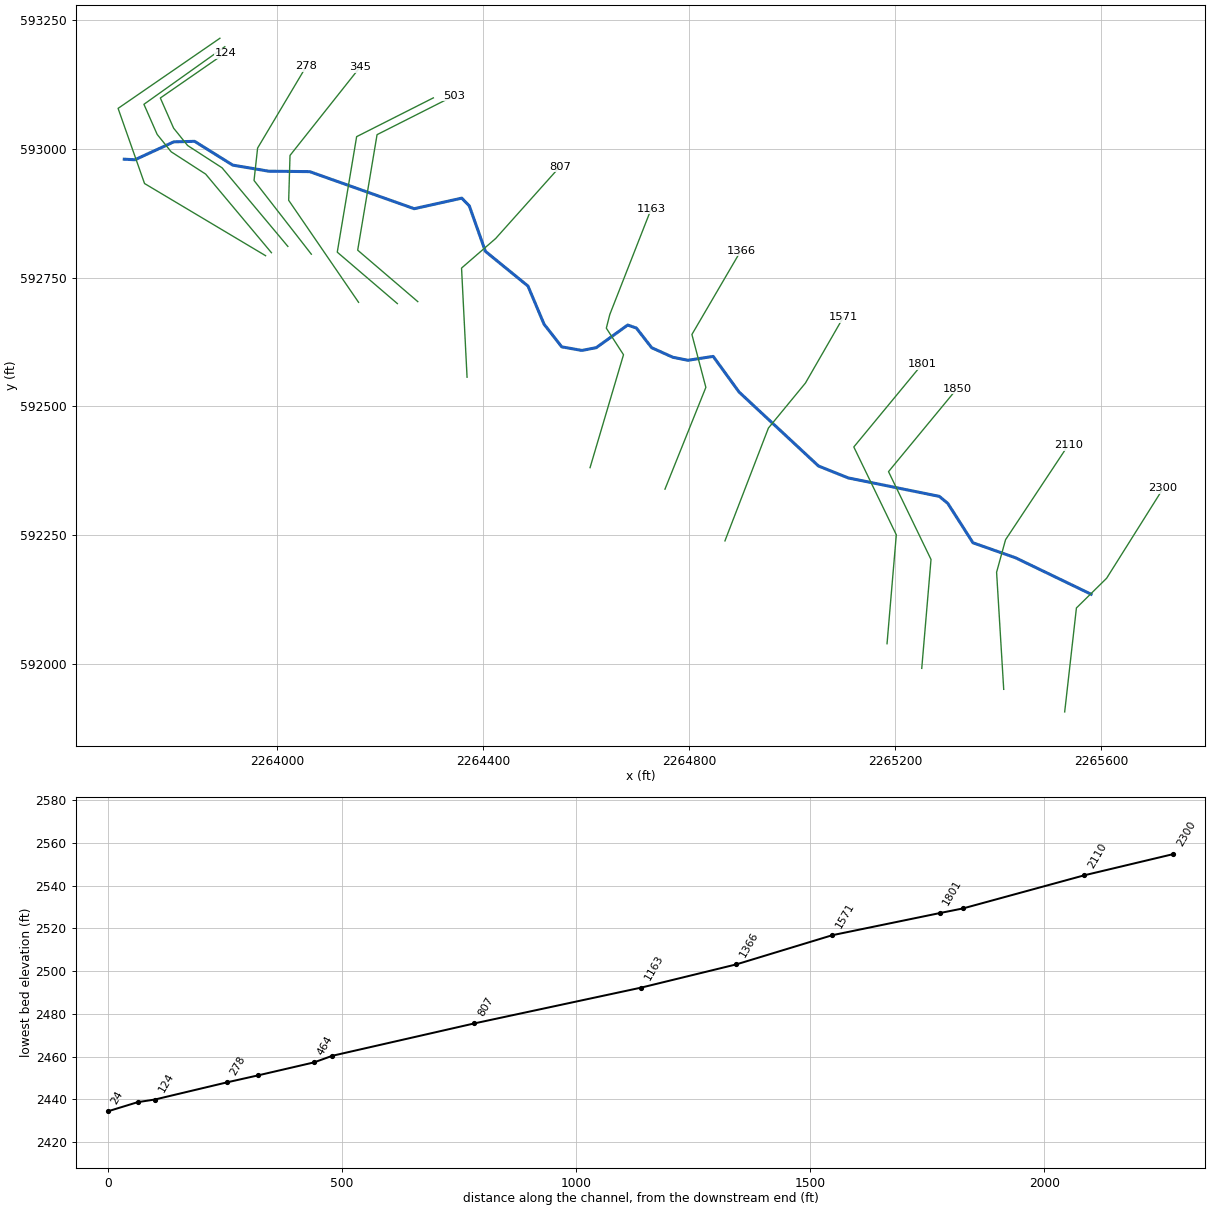
--- WMSLEYRN.prj (project) ---

Proj Title=WMSLEYRN
Current Plan=p01
Default Exp/Contr=0,0
English Units
Geom File=g01
Flow File=f01
Plan File=p01
BEGIN DESCRIPTION:
----------MODEL BY WOOD PLC 2022----------
AFH study
Randolph County, WV
HEC-RAS Version: RAS 6.2
Vertical Datum: NAVD88
Projection: NAD 1983 StatePlane West Virginia S FIPS 4702 (US Feet)
Terrain: 1-meter LIDAR (FEMA Region III 3DEP collected 2016-2018)
Land Use: 2019 NLCD
Hydrologic Method:
WV SIR2010-5033 regression equations
Additional Model Notes:
None
END DESCRIPTION:
DSS Export Rating Curves= 0
DSS Export Rating Curve Sorted= 0
DSS Export Volume Flow Curves= 0
DXF OffsetX= 0
DXF OffsetY= 0
DXF ScaleX= 0
DXF ScaleY= 0

--- WMSLEYRN.p01 (plan) ---

Plan Title=Floodplain
Program Version=6.20
Short Identifier=Floodplain
Geom File=g01
Flow File=f01
Subcritical Flow
K Sum by GR= 0
Std Step Tol= 0.01
Critical Tol= 0.01
Num of Std Step Trials= 20
Max Error Tol= 0.3
Flow Tol Ratio= 0.001
Split Flow NTrial= 30
Split Flow Tol= 0.02
Split Flow Ratio= 0.02
Log Output Level= 0
Friction Slope Method= 1
Unsteady Friction Slope Method= 2
Unsteady Bridges Friction Slope Method= 1
Parabolic Critical Depth
Global Vel Dist= 0 , 0 , 0
Global Log Level= 0
CheckData=True
Encroach Param=-1 ,0,0, 0
Mapping Interval=1HOUR
Computation Time Step Use Courant=        0
Computation Time Step Use Time Series=    0
Computation Time Step Count To Double=0
Computation Time Step Max Doubling=0
Computation Time Step Max Halving=0
Computation Time Step Residence Courant=0
Run HTab= 0
Run UNet= 0
Run Sediment= 0
Run PostProcess= 0
Run WQNet= 0
Run RASMapper=-1
UNET Theta= 0
UNET Theta Warmup= 0
UNET ZTol= 0
UNET ZSATol= 0
UNET MxIter= 0
UNET Max Iter WO Improvement= 0
UNET MaxInSteps= 0
UNET DtIC= 0
UNET DtMin= 0
UNET MaxCRTS= 0
UNET WFStab= 0
UNET SFStab= 0
UNET WFX= 1
UNET SFX= 1
UNET Gravity=32.174
UNET 1D Methodology=Finite Difference
UNET DSS MLevel= 1
UNET Pardiso=0
UNET DZMax Abort= 0
UNET Use Existing IB Tables= 0
UNET Froude Reduction=False
UNET Froude Limit= 0
UNET Froude Power= 0
UNET D1 Cores= 0
UNET WindReference=Eulerian
UNET WindDragFormulation=Hsu (1988)
UNET D2 Coriolis=0
UNET D2 Cores= 0
UNET D2 Theta= 1
UNET D2 Theta Warmup= 1
UNET D2 Z Tol= 0.01
UNET D2 Volume Tol= 0.01
UNET D2 Max Iterations= 20
UNET D2 Equation= 0
UNET D2 RampUpFraction=0.1
UNET D2 TimeSlices= 1
UNET D2 Turbulence Formulation=Non-Conservative (original)
UNET D2 Eddy Viscosity=0.3
UNET D2 Transverse Eddy Viscosity=0.1
UNET D2 Smagorinsky Mixing=0
UNET D2 BCVolumeCheck=0
UNET D2 Cores=0
UNET D2 SolverType=PARDISO (Direct)
UNET D2 Minimum Iterations= 2147483647
UNET D2 Maximum Iterations= 2147483647
UNET D2 Restart Number= 10
UNET D2 Relaxation Coeff=1.3
UNET D2 SOR Precondition Iterations= 10
UNET D2 ILUT Maximum Fill= 8
UNET D2 ILUT Tolerance=1E-08
UNET D1D2 MaxIter= 0
UNET D1D2 ZTol=0.01
UNET D1D2 QTol=0.1
UNET D1D2 MinQTol=1
Write IC File= 0
Write IC File at Fixed DateTime=0
Write IC File at Sim End=0
Echo Input=False
Echo Parameters=False
Echo Output=False
Write Detailed= 0
HDF Write Warmup=0
HDF Write Time Slices=0
HDF Flush=0
HDF Compression= 1
HDF Chunk Size= 1
HDF Spatial Parts= 1
HDF Use Max Rows=0
HDF Fixed Rows= 1
Calibration Method= 0
Calibration Iterations= 20
Calibration Max Change=0.05
Calibration Tolerance=0.2
Calibration Maximum=1.5
Calibration Minimum=0.5
Calibration Optimization Method= 1
WQ AD Non Conservative
WQ ULTIMATE=-1
WQ Max Comp Step=1HOUR
WQ Output Interval=15MIN
WQ Output Selected Increments= 0
WQ Output face flow=0
WQ Output face velocity=0
WQ Output face area=0
WQ Output face dispersion=0
WQ Output cell volume=0
WQ Output cell surface area=0
WQ Output cell continuity=0
WQ Output cumulative cell continuity=0
WQ Output face conc=0
WQ Output face dconc_dx=0
WQ Output face courant=0
WQ Output face peclet=0
WQ Output face adv mass=0
WQ Output face disp mass=0
WQ Output cell mass=0
WQ Output cell source sink temp=0
WQ Output nsm pathways=0
WQ Output nsm derived pathways=0
WQ Create Restart=0
WQ Fixed Restart=0
WQ System Summary=0
WQ Write To DSS=0
Sorting and Armoring Iterations= 10
XS Update Threshold= 0.02
Bed Roughness Predictor= 0
Hydraulics Update Threshold= 0.02
Energy Slope Method= 1
Volume Change Method= 1
Sediment Retention Method= 0
Sediment TS Multiplier= 1
Warm Up Method= 0
XS Weighting Method= 0
Number of US Weighted Cross Sections= 1
Number of DS Weighted Cross Sections= 1
Upstream XS Weight=0
Main XS Weight=1
Downstream XS Weight=0
Number of DS XS's Weighted with US Boundary= 1
Upstream Boundary Weight= 1
Weight of XSs Associated with US Boundary= 0
Number of US XS's Weighted with DS Boundary= 1
Downstream Boundary Weight= 0.5
Weight of XSs Associated with DS Boundary= 0.5
Percentile Method= 0
Sediment Output Level= 3
Mass or Volume Output= 0
Output Increment Type= 1
Profile and TS Output Increment= 1
Transport Output Increment 1
XS Output Flag= 0
XS Output Increment= 10
Read HDF5 Sediment Hotstart= 0
Sediment Hotstart Type= 0
Write Gradation File= 0
Read Gradation Hotstart= 0
Write HDF5 File= 1
Write Binary Output= 1
Write DSS Sediment File= 0
DSS Sediment Output Type= 1
SV Curve= 0
Specific Gage Flag= 0
Subcell Erosion Methods= 0
Subcell Deposition Methods= 0
Advection Scheme= 1
Matrix Solver= 0
Implicit Weighting Factor= 1
Maximum Outer Loop Convergence Iterations= 5
Convergence Maximum Absolute= 0.001
Convergence RMSE= 0.0001
Grain Fractions Max Abs Error= 0.001
Max Subgrid Regions= 1
Max Subgrid Length Scale= 3.402823E+38
Initial Layer Thickness= 3.402823E+38
Min Layer Thickness= 3.402823E+38
Max Layer Thickness= 3.402823E+38
Number of Layers= 5

--- WMSLEYRN.f01 (steady flow) ---

Flow Title=Flow
Program Version=6.20
Number of Profiles= 1
Profile Names=P100yr
River Rch & RM=WMSLEYRN,Main            ,2300
     313
Boundary for River Rch & Prof#=WMSLEYRN,Main            , 1
Up Type= 0
Dn Type= 3
Dn Slope=0.067504
DSS Import GetInterval= 0
DSS Import GetPeak= 0
DSS Import FillOption= 0

--- WMSLEYRN.g01 (geometry) ---

Geom Title=Geometry
Program Version=6.20

River Reach=WMSLEYRN        ,Main
Reach XY= 30
2265580.40800002592135.5290000142265433.68399999592206.249000013
     2265350.906592235.3920000052265302.09800002592311.844000012
2265285.52200001592325.4899999952265108.71100003592361.286000013
     2265050.911592384.4130000172264896.73100001592527.947999999
2264846.44200002592597.1490000192264797.43900003592589.622000009
2264767.92500001592595.525000006     2264726.955592614.029000014
2264697.23100004592652.2039999962264680.42500004592658.025000006
2264619.44500001592614.1749999972264591.53600001592608.719000012
2264552.29700004592615.666000009     2264517.992592659.620000005
     2264486.675592733.7189999972264404.03600003592801.079999998
2264372.78600003592889.2750000062264358.11900003592904.320999995
2264265.80200002592883.8240000012264062.75900002592955.780000016
2263983.20299999592956.6360000222263913.36300002592968.415999994
     2263839.264593014.5869999982263798.82800002593013.580000013
2263723.48100002592978.857999995      2263702.73        592979.9

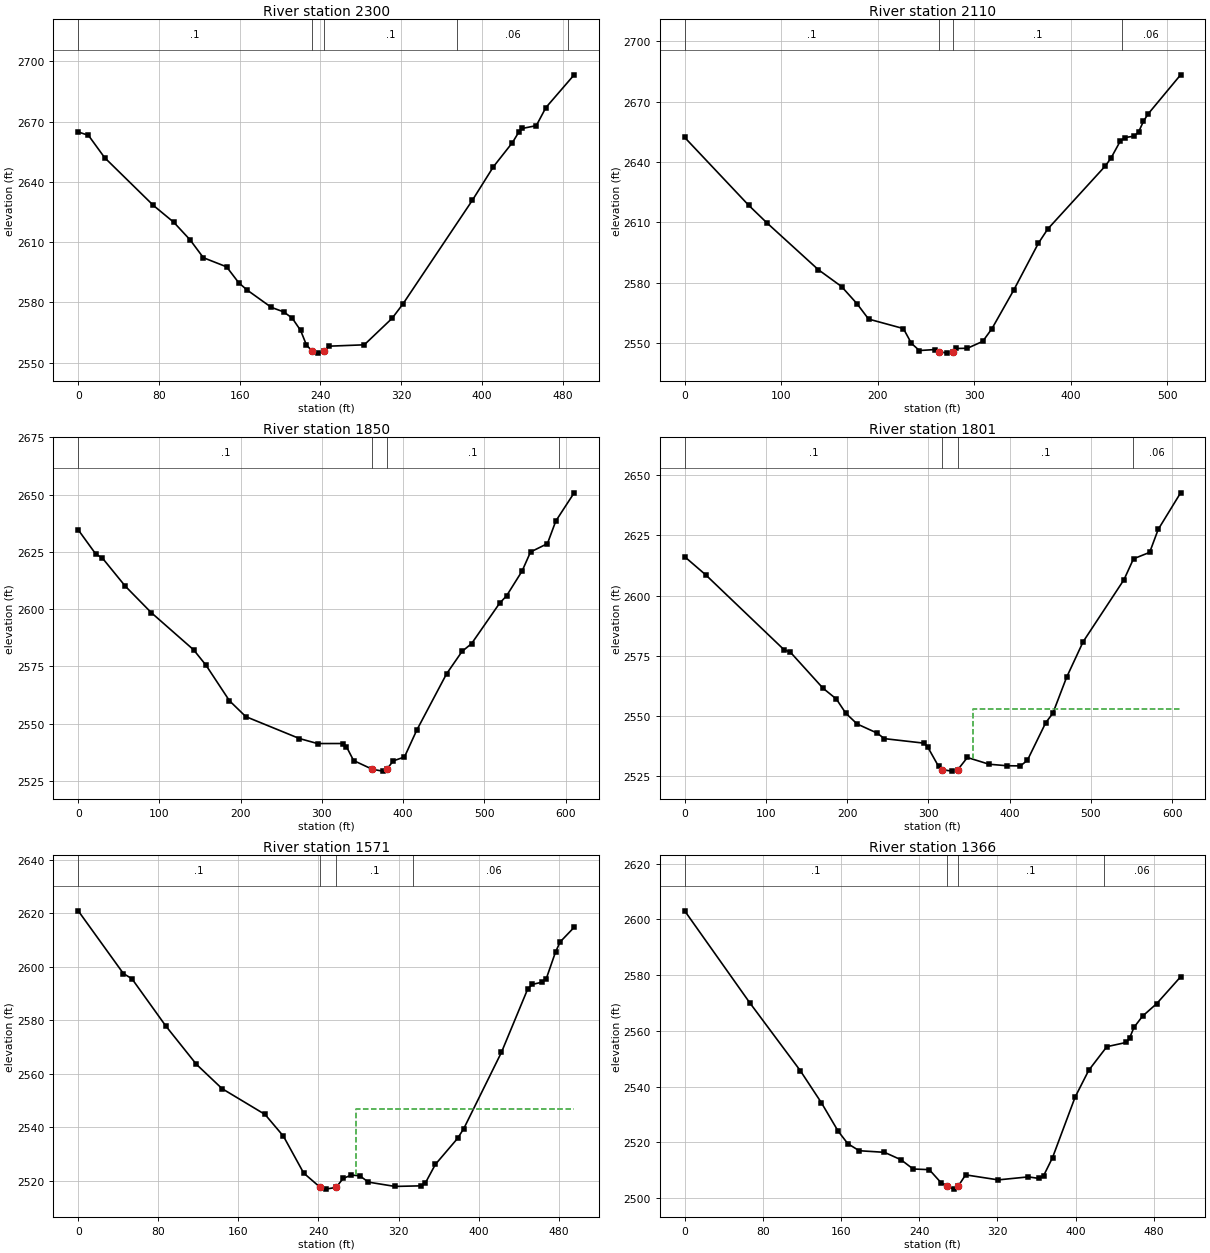
Type RM Length L Ch R = 1 ,2300    ,186.3,190.1,192.8
XS GIS Cut Line= 4
2265529.06340064 591907.123071592265551.85506878592108.873417613
2265610.51584777592166.5335519862265720.22842358592340.852678876
#Sta/Elev= 30
       0 2664.81    10.1 2663.14    26.2 2652.01    74.5 2628.25    94.7 2619.86
   110.8 2611.15     124 2602.25     147 2597.71   159.1 2589.74   167.4 2586.15
   191.3 2577.55   203.5 2575.31     212  2572.2   220.3 2566.09   226.1 2558.82
  231.752555.792   237.4 2554.78  243.212555.793   248.7 2558.24   283.4 2558.92
   310.9 2572.07   321.5  2579.1   390.5 2630.85   411.3  2647.5   430.2 2659.55
   436.3 2664.61   439.7 2666.53   453.8 2667.95   463.3 2676.94   491.3 2693.23
#Mann= 5 ,-1,0
       0      .1       0  231.75    .045       0  243.21      .1       0
  375.29     .06       0  485.29      .1       0
Bank Sta=231.75,243.21
XS Rating Curve= 0 ,0
Exp/Cntr(USF)=0,0
Exp/Cntr=0.3,0.1

Type RM Length L Ch R = 1 ,2110    ,253.5,259.1,265.1
XS GIS Cut Line= 4
2265410.64312178591950.9265896432265396.82135228592178.217910382
2265414.18252695592241.2516830792265536.25561359 592425.31300096
#Sta/Elev= 30
       0 2652.23    66.4 2618.43    85.1 2609.76   138.5  2586.4   162.6    2578
   178.6 2569.45   190.6 2561.81   226.7 2557.08   234.9 2549.79   243.2 2546.15
   259.8 2546.65  263.79 2545.57   271.9 2544.86  277.742545.569   281.6 2547.17
     293 2547.28   308.9 2550.71   318.4    2557     341  2576.2   366.6 2599.57
   376.3 2606.64   435.9 2637.99   441.7 2641.82   451.4 2650.34   456.2 2652.17
   465.8 2652.84   470.4 2654.89   475.4 2660.17   480.2 2663.85     514 2683.39
#Mann= 4 ,-1,0
       0      .1       0  263.79    .045       0  277.74      .1       0
  453.09     .06       0
Bank Sta=263.79,277.74
XS Rating Curve= 0 ,0
Exp/Cntr(USF)=0,0
Exp/Cntr=0.3,0.1

Type RM Length L Ch R = 1 ,1850    ,48.2,49.9,49.2
XS GIS Cut Line= 4
2265251.45819375591991.6054624442265269.47010188592203.008384219
2265186.93765091592373.4910398972265320.00285981592534.597488488
#Sta/Elev= 30
       0  2634.6    21.7 2623.98    29.7 2622.31    57.8 2610.08    89.9 2598.49
   142.1 2582.25   157.5 2575.46   186.2 2560.04   206.3 2553.13   272.4 2543.56
   294.6 2541.39   325.7  2541.4   330.1 2540.07     339 2533.98  362.022530.168
   374.6 2529.36   379.8 2530.17   387.9 2533.84   401.6 2535.52   416.7 2547.19
   453.4 2571.77   472.6 2581.61   484.2 2584.95   518.7 2602.57   527.3 2605.81
   546.4 2616.61   556.8 2624.93   577.6 2628.57   587.9 2638.42   610.5 2650.73
#Mann= 4 ,-1,0
       0      .1       0  362.02    .045       0   379.8      .1       0
  591.58     .06       0
Bank Sta=362.02,379.8
XS Rating Curve= 0 ,0
Exp/Cntr(USF)=0,0
Exp/Cntr=0.3,0.1

Type RM Length L Ch R = 1 ,1801    ,238.6,229.5,219.2
XS GIS Cut Line= 4
  2265184.054605592039.4750645842265202.06651313592250.877986359
2265119.53406216592421.3606420372265252.59927106592582.467090628
#Sta/Elev= 30
       0 2616.12    25.8 2608.63   122.1  2577.6   130.2 2576.48   170.3 2561.56
   186.7 2557.09   198.4 2551.16   212.3 2546.73   236.9 2542.95   245.8 2540.65
   294.7 2538.77   299.2 2537.16   312.5 2529.15  316.782527.768   329.1 2527.17
   336.22527.766     348 2532.83   374.7 2530.03   396.9  2529.4   413.3 2529.34
   421.8 2531.62   444.5 2547.28   453.2 2551.16   470.1 2566.06   490.5 2580.85
   540.8 2606.61   552.5 2615.26   572.4 2617.93   582.9 2627.45   610.5 2642.63
#Mann= 4 ,-1,0
       0      .1       0  316.78    .045       0   336.2      .1       0
  551.58     .06       0
#XS Ineff= 2 , 0
                           354.8         2552.83
Permanent Ineff=
       F       F
Bank Sta=316.78,336.2
XS Rating Curve= 0 ,0
Exp/Cntr(USF)=0,0
Exp/Cntr=0.3,0.1

Type RM Length L Ch R = 1 ,1571    ,201.8,204.8,211.6
XS GIS Cut Line= 4
2264869.27356348592239.0682267872264953.67410976592458.063967191
2265025.59116683592545.4458737732265099.25157586 592673.25348807
#Sta/Elev= 30
       0 2620.99    45.1 2597.53    53.7 2595.54    87.4 2577.93     118 2563.56
   143.7 2554.43   186.6 2544.78     205 2536.63   225.2 2522.84  241.762517.474
   247.2 2516.82  257.642517.473   264.6 2520.81   272.8 2522.08   281.3 2521.81
   289.8 2519.45   316.4 2517.83   342.3 2518.05   346.7 2519.07   356.8 2526.09
   378.9 2535.79   385.1 2539.44   422.8 2568.05   449.1 2591.81   453.7 2593.46
     463 2594.25   467.6 2595.64   476.8 2605.58   481.4 2609.35   495.4 2614.82
#Mann= 4 ,-1,0
       0      .1       0  241.76    .045       0  257.64      .1       0
   334.7     .06       0
#XS Ineff= 2 , 0
                          277.62         2546.83
Permanent Ineff=
       F       F
Bank Sta=241.76,257.64
XS Rating Curve= 0 ,0
Exp/Cntr(USF)=0,0
Exp/Cntr=0.3,0.1

Type RM Length L Ch R = 1 ,1366    ,198.3,203.2,201.9
XS GIS Cut Line= 4
2264752.79768284592339.4774316892264832.20011374592537.038241906
2264805.09328651592639.6765370052264900.23319414592802.368421926
#Sta/Elev= 30
       0 2603.05    66.5  2570.1   118.2 2545.75   139.8 2534.24     157    2524
   166.9  2519.5   178.6 2516.96   204.4 2516.39   221.3 2513.73   233.8  2510.4
   250.3 2510.17   262.7 2505.34  268.652504.277   275.1 2503.18  279.932504.276
   287.5  2508.3   320.8  2506.5   351.7 2507.57   362.5 2507.02   367.2 2507.93
   376.4 2514.46   399.6 2536.25   413.5 2545.84     432  2554.3     452 2555.83
   455.2 2557.34   459.8 2561.24   468.6 2565.27     483 2569.74   507.5 2579.37
#Mann= 4 ,-1,0
       0      .1       0  268.65    .045       0  279.93      .1       0
  429.08     .06       0
Bank Sta=268.65,279.93
XS Rating Curve= 0 ,0
Exp/Cntr(USF)=0,0
Exp/Cntr=0.3,0.1

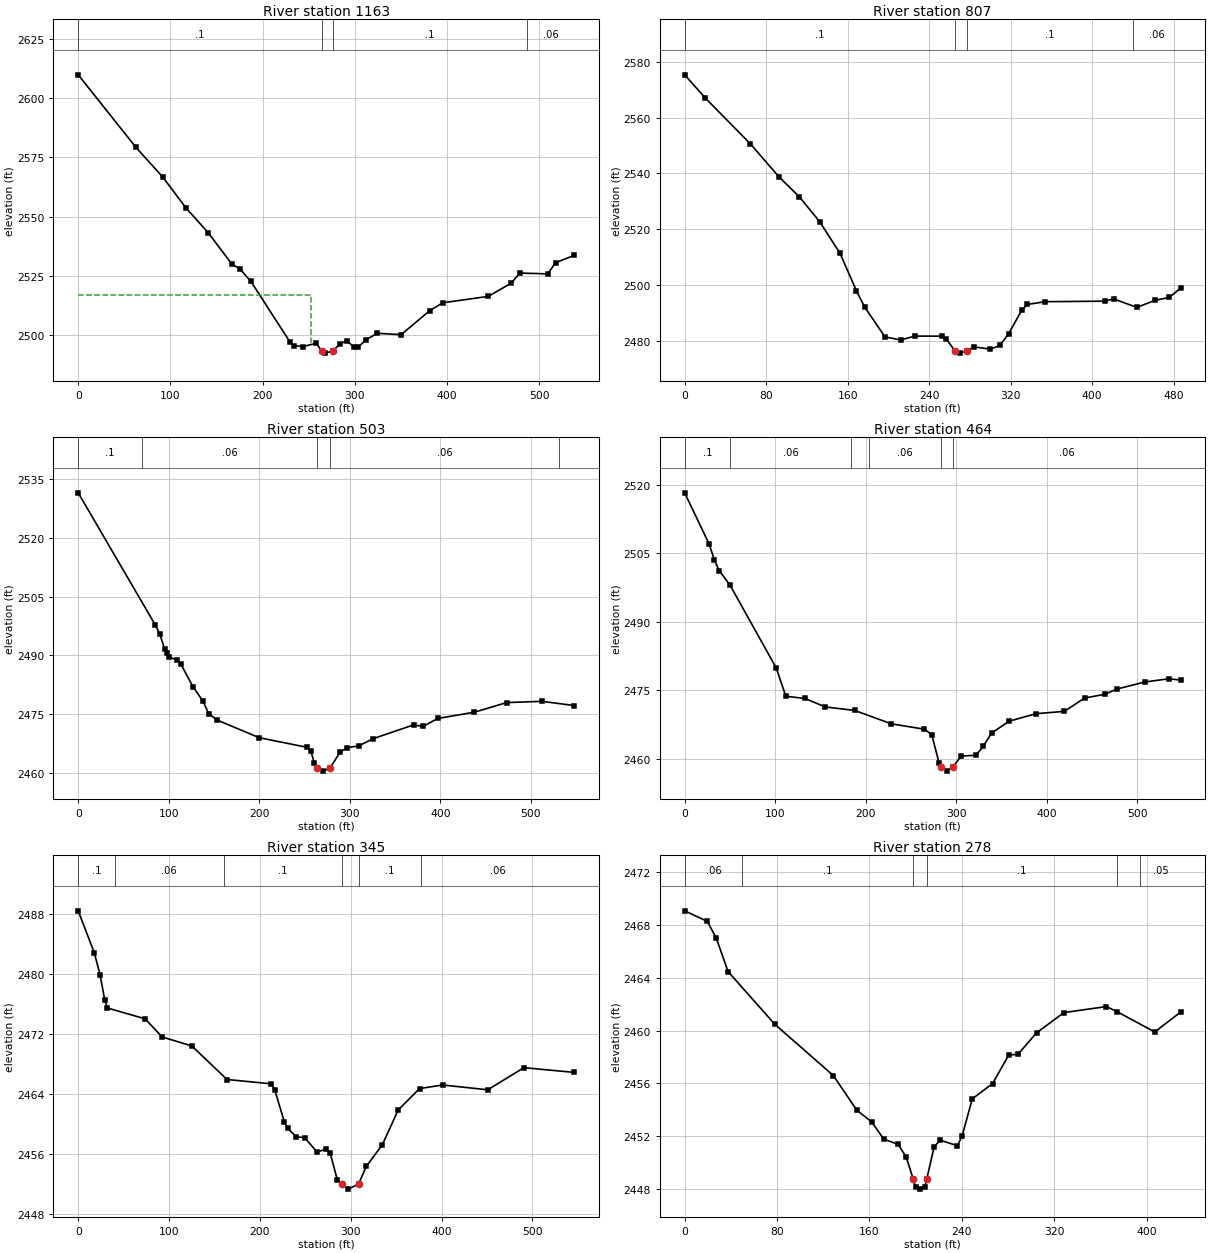
Type RM Length L Ch R = 1 ,1163    ,364.9,356.4,348.2
XS GIS Cut Line= 5
2264607.28183964592381.1853097242264672.24850741592600.382779194
2264638.88315603592651.9609499742264645.61950299592678.442928707
2264726.18791018592883.887275045
#Sta/Elev= 30
       0 2609.88    62.6 2579.26    91.8 2566.66   116.8 2553.72     141 2543.19
   166.9 2529.86   175.2 2527.99   187.4 2522.58   229.6 2497.13   234.3 2495.46
   243.9 2495.08   258.2 2496.47  264.352493.184   267.7 2492.31   276.32493.184
   284.2  2496.3   291.3 2497.43   299.6 2494.88   303.7 2494.74   311.9 2497.91
   324.6 2500.69   350.4 2500.11   381.3 2510.22   395.5 2513.58   444.9 2516.28
   469.6 2521.83   479.3 2526.15   509.4 2525.78     518 2530.53   538.1 2533.61
#Mann= 4 ,-1,0
       0      .1       0  264.35    .045       0   276.3      .1       0
  487.38     .06       0
#XS Ineff= 2 , 0
          252.56 2516.93
Permanent Ineff=
       F       F
Bank Sta=264.35,276.3
XS Rating Curve= 0 ,0
Exp/Cntr(USF)=0,0
Exp/Cntr=0.3,0.1

Type RM Length L Ch R = 1 ,807     ,300,303.2,307.7
XS GIS Cut Line= 4
2264368.41436655592556.7559870112264357.71247563592768.595595231
2264423.92021052592825.9273736852264548.78550635592965.433522155
#Sta/Elev= 30
       0 2575.34    20.4 2566.96    64.5  2550.6    92.5 2538.79   112.6 2531.58
   132.6 2522.66   152.6 2511.28   168.6 2497.89   176.6 2492.13   196.7 2481.37
   212.1 2480.28   225.9 2481.67   252.4 2481.64   256.8 2480.74  265.132476.393
   270.1 2475.56  276.782476.393   284.2 2477.79   300.1 2476.98   309.4  2478.3
   318.1 2482.55   330.9 2490.93   336.3 2493.01   354.1    2494   412.7 2494.19
   421.1    2495     444 2491.96     462 2494.52   475.8 2495.54   486.9 2498.86
#Mann= 4 ,-1,0
       0      .1       0  265.13    .045       0  276.78      .1       0
  439.69     .06       0
Bank Sta=265.13,276.78
XS Rating Curve= 0 ,0
Exp/Cntr(USF)=0,0
Exp/Cntr=0.3,0.1

Type RM Length L Ch R = 1 ,503     ,39.5,39.3,39.3
XS GIS Cut Line= 4
 2264272.7274962592703.4974251222264156.01033149592803.321315987
2264193.63625959593027.541132393 2264342.6042198593102.792988584
#Sta/Elev= 30
       0 2531.49    84.9 2497.84    90.2 2495.37    95.5 2491.57      98 2490.56
   100.7 2489.56   109.4 2488.77   113.4 2487.74     127 2481.88   137.8  2478.3
   144.1  2475.1   153.6 2473.44   200.1 2468.95   252.8  2466.5   256.9 2465.57
   260.9 2462.45  264.222461.177     270 2460.42  277.992461.179   289.3 2465.27
   297.4 2466.45   309.6 2466.84   325.8 2468.71   370.4 2472.22   380.9 2471.84
   397.2 2473.87   437.6 2475.47   473.3 2477.93   512.1 2478.24   547.8 2477.17
#Mann= 5 ,-1,0
       0      .1       0      70     .06       0  264.22    .045       0
  277.99     .06       0  530.94      .1       0
Bank Sta=264.22,277.99
XS Rating Curve= 0 ,0
Exp/Cntr(USF)=0,0
Exp/Cntr=0.3,0.1

Type RM Length L Ch R = 1 ,464     ,118.1,119.1,120.7
XS GIS Cut Line= 4
2264233.06976799592699.6469872882264116.35260328592799.470878154
2264153.97853138 593023.690694562264302.94649159593098.942550751
#Sta/Elev= 30
       0 2518.18      27 2506.99    32.8 2503.52      38 2501.19      50 2498.03
   101.2 2479.84   111.7  2473.7   132.8 2473.21   155.3 2471.36   187.8 2470.59
   228.3 2467.66   264.8 2466.49   272.9  2465.3     281  2459.1   283.4 2458.29
   289.2 2457.32  296.582458.291   305.4 2460.61   321.7 2460.79   329.7 2462.71
     339 2465.63   358.1 2468.22   387.9 2469.88   419.4 2470.39   441.7  2473.3
     464 2474.12   477.5 2475.27   508.4 2476.82   535.1 2477.52   547.8 2477.22
#Mann= 6 ,-1,0
       0      .1       0      50     .06       0  183.58      .1       0
  203.58     .06       0   283.4    .045       0  296.58     .06       0
Bank Sta=283.4,296.58
XS Rating Curve= 0 ,0
Exp/Cntr(USF)=0,0
Exp/Cntr=0.3,0.1

Type RM Length L Ch R = 1 ,345     ,67.2,66.8,66.4
XS GIS Cut Line= 4
2264157.73525937592702.0904072412264022.00035145592900.101437324
2264024.57872977592987.2189592632264160.54914624593158.519068071
#Sta/Elev= 30
       0 2488.39    17.7 2482.79      24 2479.89    29.2  2476.5    32.1 2475.43
    73.5 2473.99    92.5 2471.56     125 2470.37   163.8 2465.89   212.3 2465.32
   216.3 2464.53   226.8 2460.27   230.6 2459.36   240.1 2458.24   249.1 2458.15
   262.7 2456.25   273.2 2456.58   277.2 2456.14   285.2 2452.52   290.72451.937
   297.2 2451.27  308.542451.937   317.1  2454.3   334.8  2457.2   352.3 2461.84
   375.7 2464.68   401.2 2465.16   450.8 2464.52   490.6 2467.47   545.9 2466.84
#Mann= 6 ,-1,0
       0      .1       0      40     .06       0     160      .1       0
   290.7    .045       0  308.54      .1       0  377.22     .06       0
Bank Sta=290.7,308.54
XS Rating Curve= 0 ,0
Exp/Cntr(USF)=0,0
Exp/Cntr=0.3,0.1

Type RM Length L Ch R = 1 ,278     ,150.8,154.2,160.9
XS GIS Cut Line= 4
2264065.98292084592795.5252555762263954.71767633592938.580569947
2263961.62856109593001.4696211932264056.30768219593160.419970495
#Sta/Elev= 30
       0 2469.09    19.6 2468.29    27.4 2467.01    37.6 2464.48    78.1 2460.48
   128.8 2456.59   149.1 2453.96   162.1 2453.07   172.3 2451.78   184.9 2451.37
   191.9  2450.4  197.772448.786   199.9 2448.12     204 2447.98     208 2448.17
  209.772448.786     216 2451.18   221.2  2451.7   236.2 2451.27   240.2    2452
   249.1 2454.83   266.6 2455.98   280.7 2458.16   288.6  2458.2   304.7 2459.83
   328.4 2461.37   365.2 2461.83   374.5 2461.44   407.1  2459.9   429.5 2461.41
#Mann= 6 ,-1,0
       0     .06       0      50      .1       0  197.77    .045       0
  209.77      .1       0   374.5     .06       0   394.5     .05       0
Bank Sta=197.77,209.77
XS Rating Curve= 0 ,0
Exp/Cntr(USF)=0,0
Exp/Cntr=0.3,0.1

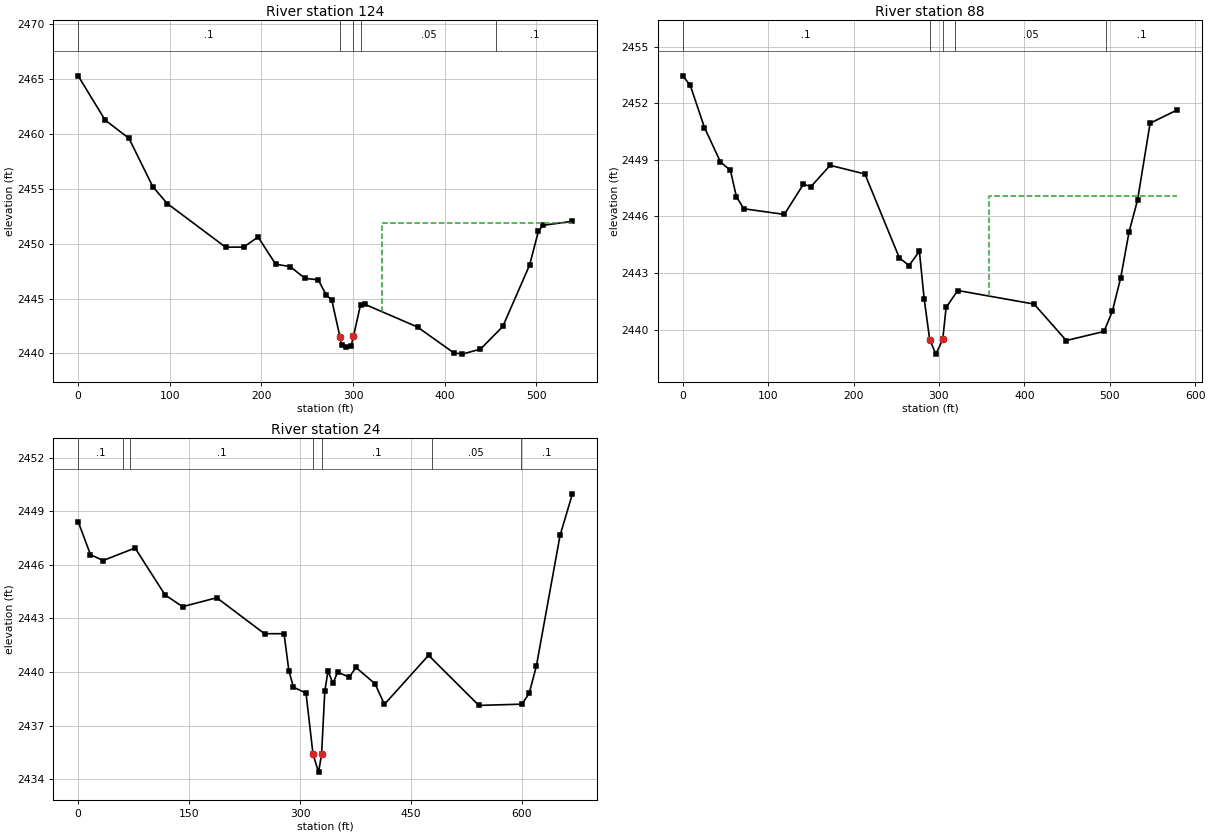
Type RM Length L Ch R = 1 ,124     ,35.8,36.6,35.8
XS GIS Cut Line= 6
2264020.38210408592810.6607857612263892.66480733592963.195069659
2263825.65894204593006.5221705252263798.45355312 593040.27700492
 2263772.7595747593098.7182107392263898.64877559593185.858442008
#Sta/Elev= 30
       0 2465.31    29.4 2461.28    55.5 2459.61    81.5  2455.2    97.2 2453.67
   160.9 2449.69   180.7  2449.7   196.3 2450.62   215.5 2448.14   231.3 2447.92
   247.6 2446.84   261.9 2446.72   270.8 2445.32   276.7 2444.88  285.65 2441.52
   287.6 2440.78   292.6 2440.56   297.8 2440.68   300.4 2441.55   308.1 2444.44
   313.2 2444.47   370.3 2442.41   409.8 2440.06   419.1 2439.94     439  2440.4
   463.3 2442.46   492.5 2448.04   502.2 2451.14   507.1 2451.68   539.3 2452.05
#Mann= 5 ,-1,0
       0      .1       0  285.65    .045       0   300.4      .1       0
  308.96     .05       0  456.15      .1       0
#XS Ineff= 1 ,-1
  331.41539.2592  2451.9
Permanent Ineff=
       F
Bank Sta=285.65,300.4
XS Rating Curve= 0 ,0
Exp/Cntr(USF)=0,0
Exp/Cntr=0.3,0.1

Type RM Length L Ch R = 1 ,88      ,66.2,63.9,61.5
XS GIS Cut Line= 6
 2263988.5111431592798.4096105182263860.79384634592950.943894416
2263793.78798105592994.2709952822263766.58259214593028.025829677
2263740.88861372593086.467035496 2263897.9237414593198.222596012
#Sta/Elev= 30
       0 2453.45     8.8 2452.94    25.4 2450.71    44.1 2448.89    55.8 2448.44
    62.8 2447.05    71.4 2446.41   118.9 2446.11   141.3 2447.71   150.1 2447.58
   172.6 2448.71   213.3 2448.25   253.6 2443.81     265  2443.4   277.1 2444.16
   282.7 2441.64  289.172439.484   296.4 2438.71  304.432439.485   308.4 2441.18
     322 2442.08   411.5 2441.36   449.1 2439.43   493.3 2439.91   503.1 2440.98
   512.9 2442.76   522.7 2445.19   532.6 2446.87   547.3 2450.94   578.9 2451.64
#Mann= 5 ,-1,0
       0      .1       0  289.17    .045       0  304.43      .1       0
  318.96     .05       0  496.15      .1       0
#XS Ineff= 2 , 0
                           358.7          2447.1
Permanent Ineff=
       F       F
Bank Sta=289.17,304.43
XS Rating Curve= 0 ,0
Exp/Cntr(USF)=0,0
Exp/Cntr=0.3,0.1

Type RM Length L Ch R = 1 ,24      ,,,
XS GIS Cut Line= 4
2263977.15497336592792.6188838072263742.06971037592932.694838974
2263690.69112162593078.5375435292263888.40877617593214.638360859
#Sta/Elev= 30
       0 2448.42    16.7 2446.57    33.7 2446.24      77 2446.94   117.5 2444.32
   141.2 2443.66   187.4 2444.16     252 2442.15   278.4 2442.15   284.9 2440.09
   291.1 2439.16   308.1 2438.83  317.592435.404   325.1 2434.41  329.132435.406
   333.5 2438.92   337.8 2440.07   344.5 2439.37   350.8    2440   366.5 2439.72
   375.7 2440.26   401.4 2439.35   414.1  2438.2   473.8 2440.94   541.8 2438.14
     600 2438.21   609.8 2438.81   619.5 2440.33   651.6 2447.65   668.3 2449.97
#Mann= 7 ,-1,0
       0      .1       0      60     .05       0      70      .1       0
  317.59    .045       0  329.13      .1       0  478.28     .05       0
  598.28      .1       0
Bank Sta=317.59,329.13
XS Rating Curve= 0 ,0
Exp/Cntr(USF)=0,0
Exp/Cntr=0.3,0.1
LCMann Table=0

Chan Stop Cuts=-1
Use User Specified Reach Order=0
Composite Channel Slope=5